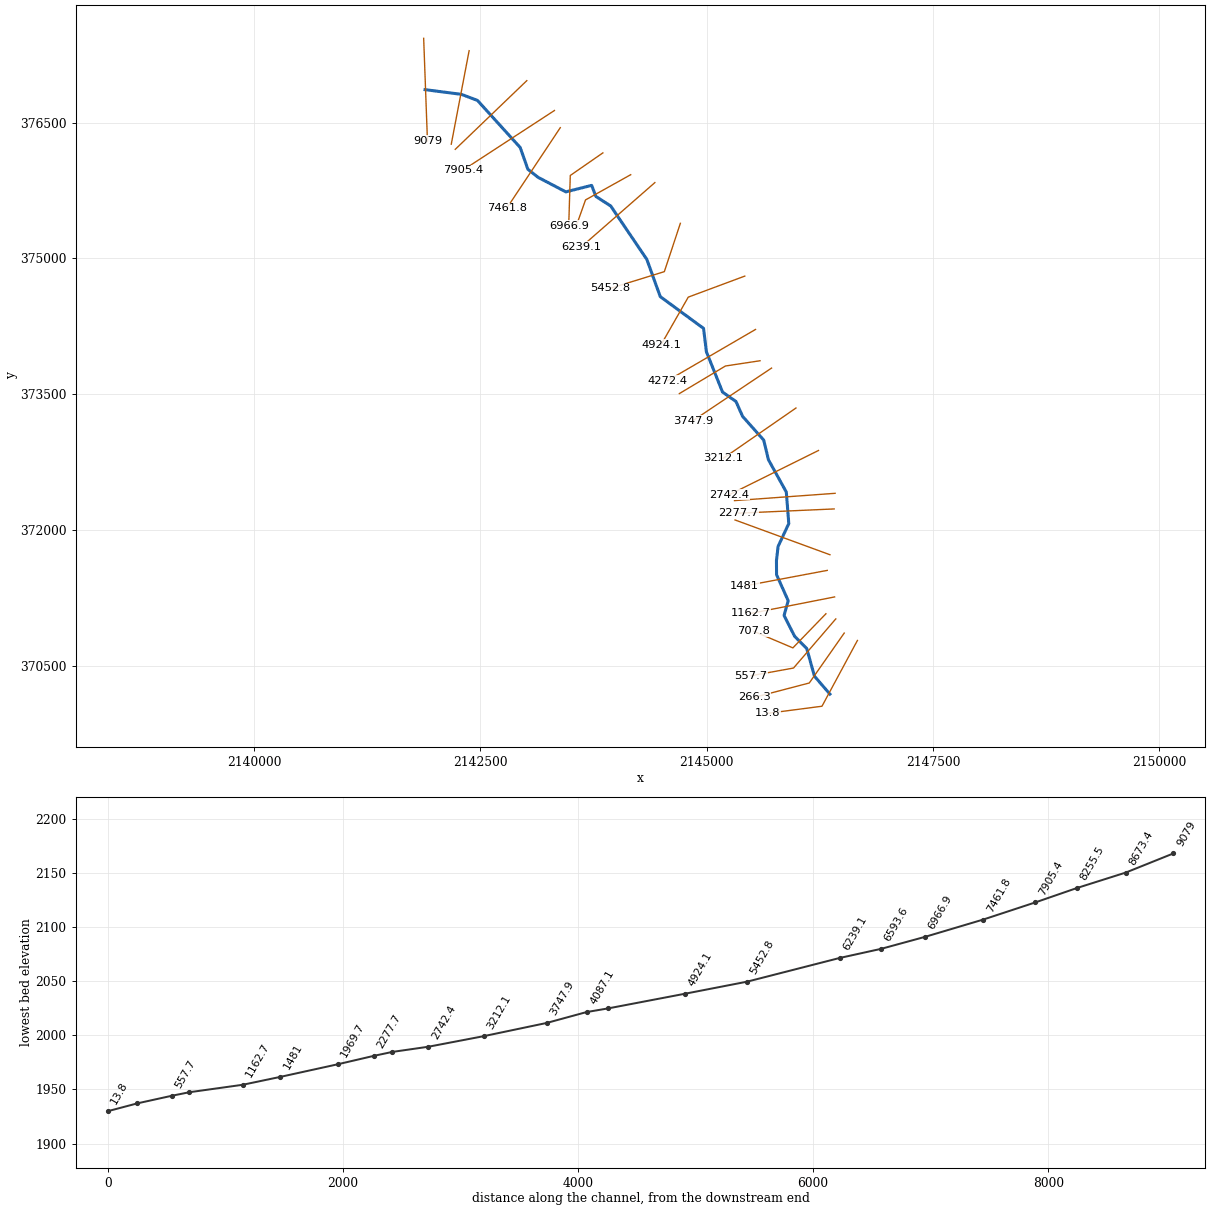
--- DryRun.prj (project) ---

Proj Title=DryRun
Current Plan=p01
Geom File=g01
Flow File=f01
Plan File=p01
DSS Export Rating Curves=0
DSS Export Rating Curve Sorted=0
DSS Export Volume Flow Curves=0
DXF OffsetX=0
DXF OffsetY=0
DXF ScaleX=0
DXF ScaleY=0

--- DryRun.p01 (plan) ---

Plan Title=Floodplain
Program Version=4.00
Geom File=g01
Flow File=f01
K Sum by GR=0
Std Step Tol=0.01
Critical Tol=0.01
Num of Std Step Trials=20
Max Error Tol=0.3
Flow Tol Ratio=0.001
Split Flow NTrial=30
Split Flow Tol=0.02
Split Flow Ratio=0.02
Log Output Level=0
Friction Slope Method=1
Unsteady Friction Slope Method=2
Unsteady Bridges Friction Slope Method=1
Global Log Level=0
CheckData=False
Run HTab=0
Run UNet=0
Run PostProcess=0
UNET Theta=0
UNET Theta Warmup=0
UNET ZTol=0
UNET ZSATol=0
UNET MxIter=0
UNET MaxInSteps=0
UNET DtIC=0
UNET DtMin=0
UNET MaxCRTS=0
UNET WFStab=0
UNET SFStab=0
UNET WFX=0
UNET SFX=0
UNET DSS MLevel=0
UNET DZMax Abort=0
UNET Convert EG Bridges=0
UNET Use Existing IB Tables=0
UNET Froude Limit=0
UNET Froude Power=0
Write IC File=0
Echo Input=False
Echo Output=False
Write Detailed=0

--- DryRun.f01 (steady flow) ---

Flow Title=NFF Regression Equation
Program Version=4.00
Number of Profiles=1
Profile Names=P100yr
River Rch & RM=DryRun,Main      ,9079
519.1744
River Rch & RM=DryRun,Main      ,8255.5
535.6406
River Rch & RM=DryRun,Main      ,6966.9
594.3168
River Rch & RM=DryRun,Main      ,6593.6
760.6633
River Rch & RM=DryRun,Main      ,4272.4
836.7404
River Rch & RM=DryRun,Main      ,557.7
898.5345
River Rch & RM=DryRun,Main      ,266.3
1112.312
Boundary for River Rch & Prof#=DryRun,Main      ,1
Up Type=0
Dn Type=3
Dn Slope=0.023537

--- DryRun.g01 (geometry) ---

Geom Title=USGS 10m DEM
Program Version=4.10

River Reach=DryRun          ,Main
Reach XY= 30
     2141889.341      376864.474     2142291.273      376812.448
     2142468.059      376745.337     2142940.122      376225.151
     2143024.682      375985.136     2143138.039      375895.724
     2143444.029      375735.568     2143729.185      375807.183
      2143776.06      375684.787     2143939.587      375579.685
      2144338.56      374989.474     2144486.824      374578.652
     2144964.862      374227.756     2144996.112      373971.245
     2145174.226      373524.753     2145322.935      373420.464
     2145395.852      373256.401     2145629.339      372993.938
     2145681.538      372777.108     2145878.924      372420.464
     2145906.319      372072.225     2145788.032      371819.223
     2145770.114      371662.885     2145771.252       371507.48
     2145899.758      371219.943     2145854.185      371057.182
     2145970.653      370827.298     2146104.185      370692.599
     2146190.122       370386.61     2146360.376      370188.709

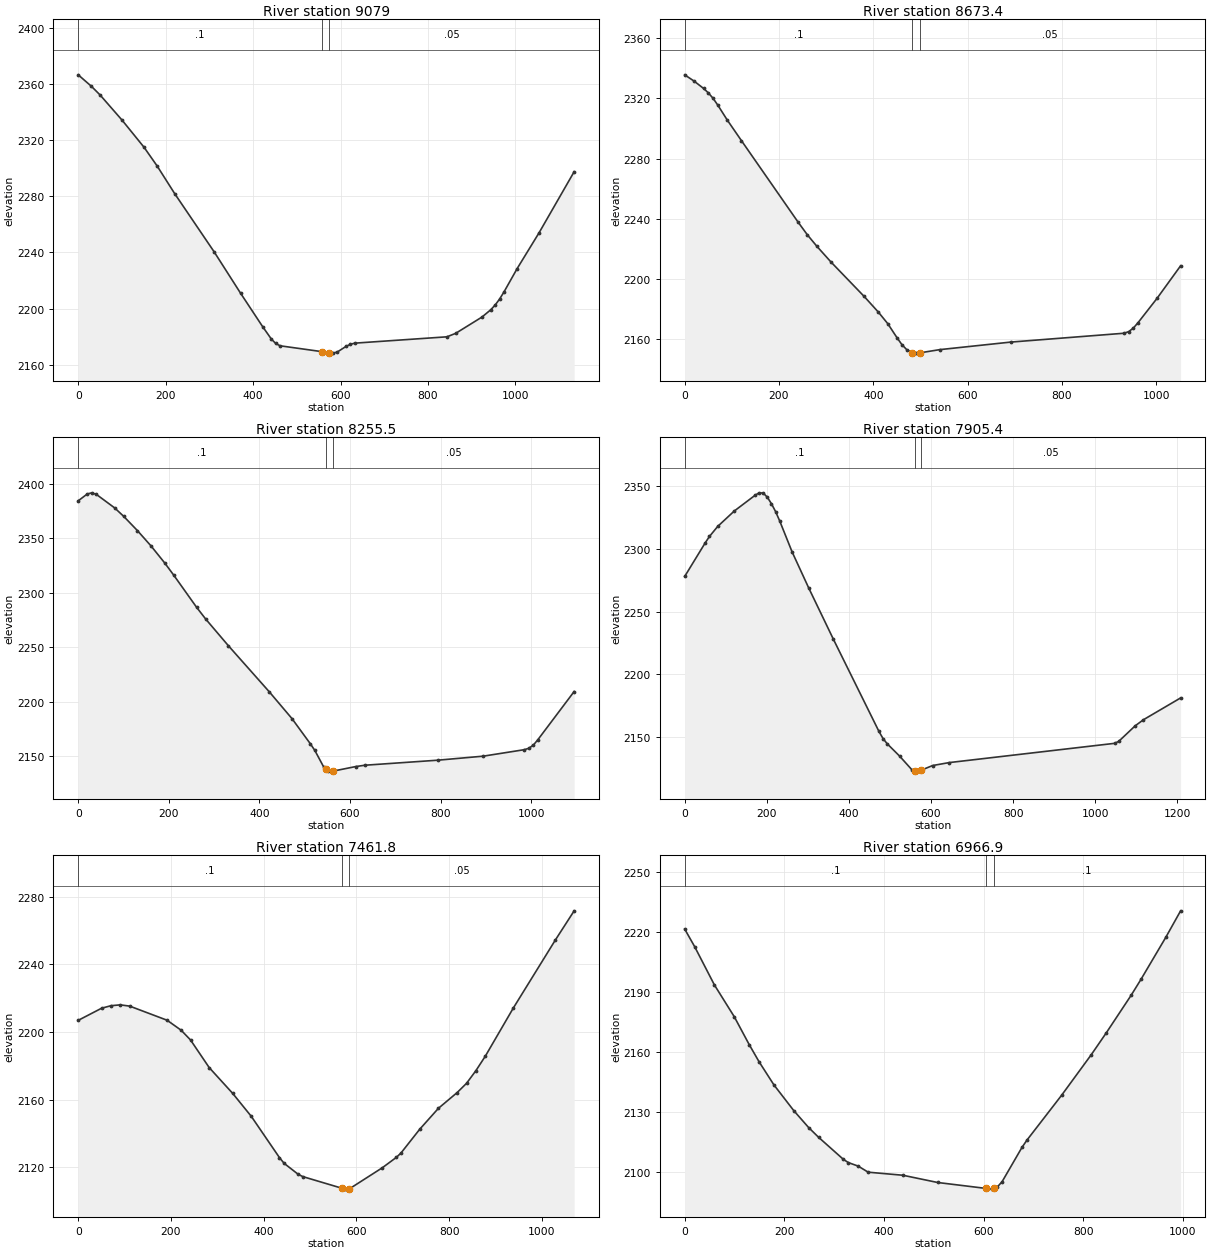
Type RM Length L Ch R = 1 ,9079    ,410.6,405.6,400.6
XS GIS Cut Line= 2
     2141873.908      377431.148     2141915.695      376297.682
#Sta/Elev= 30
       0 2366.43    30.1 2358.28    50.2 2352.03   100.4 2334.14   150.6 2314.85
   180.7 2301.45   220.8 2281.79   311.2 2240.28   371.4 2210.95   421.6 2187.27
   441.6  2178.4   451.7 2175.22   461.7 2173.56   557.9 2169.37   572.9 2168.52
   582.2 2168.34   592.2 2169.08   612.3 2173.09   622.3  2174.6   632.4 2175.44
   843.2 2179.95   863.2 2182.41   923.4 2194.02   943.5 2199.21   953.6  2202.6
   963.6 2206.79   973.6 2211.82  1003.8 2228.51  1053.9 2253.97  1134.2 2297.47
#Mann= 3 , 0 , 0
       0      .1       0   557.9    .045       0   572.9     .05       0
Bank Sta=557.9,572.9
XS Rating Curve= 0 ,0
Exp/Cntr=0.3,0.1

Type RM Length L Ch R = 1 ,8673.4  ,431.7,417.9,403.9
XS GIS Cut Line= 2
     2142375.907      377294.766      2142178.59      376261.751
#Sta/Elev= 30
       0 2335.65      20 2331.47    40.1 2326.59    50.1 2323.67    60.1 2320.07
    70.1 2315.57    90.2 2305.63   120.2 2291.97   240.4 2237.76   260.4 2229.18
   280.4 2221.63   310.5 2211.12   380.6 2188.32   410.7  2177.9   430.7  2170.2
   450.7 2160.65   460.7 2156.26   470.8 2152.97   480.8 2151.08   483.1 2150.97
   490.8 2150.62   498.1 2150.78   540.9 2152.94   691.1 2157.95   931.5 2163.84
   941.5 2164.89   951.5 2167.28   961.6 2170.94  1001.6    2187  1051.7 2208.69
#Mann= 3 , 0 , 0
       0      .1       0   483.1    .045       0   498.1     .05       0
Bank Sta=483.1,498.1
XS Rating Curve= 0 ,0
Exp/Cntr=0.3,0.1

Type RM Length L Ch R = 1 ,8255.5  ,353.9,350.1,346.1
XS GIS Cut Line= 2
     2143012.693      376963.669     2142222.969      376205.519
#Sta/Elev= 30
       0 2384.18    20.1 2390.48    30.1  2391.5    40.2 2390.03    80.4 2377.68
   100.4 2369.93   130.6  2356.9   160.7 2342.79   190.8 2327.24   210.9 2315.96
   261.1 2286.63   281.2 2275.83   331.4  2251.3   421.8 2208.97     472 2184.34
   512.2 2161.44   522.3 2155.22   542.4 2139.62   547.4 2138.04   552.4 2136.45
   562.4 2136.24   612.6 2140.43   632.7 2141.65   793.4 2146.26   893.9 2149.96
   984.3 2155.88   994.3 2157.14  1004.4    2160  1014.4 2164.95  1094.7 2209.27
#Mann= 3 , 0 , 0
       0      .1       0   547.4    .045       0   562.4     .05       0
Bank Sta=547.4,562.4
XS Rating Curve= 0 ,0
Exp/Cntr=0.3,0.1

Type RM Length L Ch R = 1 ,7905.4  ,434.3,443.7,452.9
XS GIS Cut Line= 2
     2143318.254      376634.208     2142306.266       375974.48
#Sta/Elev= 30
       0 2278.01    50.3 2304.91    60.4 2309.89    80.5 2317.86   120.8  2330.1
   171.1 2342.53   181.2 2344.58   191.3 2344.41   201.3  2341.1   211.4 2335.87
   221.5 2329.61   231.5 2322.18   261.7 2297.53     302 2268.94   362.4 2227.92
   473.2 2154.67   483.2 2148.95   493.3 2144.86   523.5 2135.03   553.7 2124.06
   560.5 2123.39   563.8 2123.07   575.5 2123.74     604 2127.53   644.3 2129.87
    1047 2145.18    1057  2146.7  1097.3 2159.12  1117.4 2163.97    1208 2181.34
#Mann= 3 , 0 , 0
       0      .1       0   560.5    .045       0   575.5     .05       0
Bank Sta=560.5,575.5
XS Rating Curve= 0 ,0
Exp/Cntr=0.3,0.1

Type RM Length L Ch R = 1 ,7461.8  ,482.2,494.9,507.8
XS GIS Cut Line= 2
     2143382.807       376444.56     2142790.855      375553.729
#Sta/Elev= 30
       0 2206.97    50.4 2214.14    70.6 2215.63    90.8 2216.13     111 2215.39
   191.7 2207.04     222 2201.13   242.2 2195.39   282.5 2179.04     333 2163.84
   373.3  2150.2   433.9 2125.87     444 2122.45   474.2 2115.99   484.3 2114.59
   569.5 2107.64   575.2 2107.18   584.5 2107.29   655.9 2119.82   686.1 2125.94
   696.2 2128.56   736.6 2142.61     777    2155   817.3 2164.28   837.5 2169.74
   857.7 2177.22   877.9 2185.74   938.4 2214.26  1029.2 2254.53  1069.6 2271.73
#Mann= 3 , 0 , 0
       0      .1       0   569.5    .045       0   584.5     .05       0
Bank Sta=569.5,584.5
XS Rating Curve= 0 ,0
Exp/Cntr=0.3,0.1

Type RM Length L Ch R = 1 ,6966.9  ,396.4,373.3,348.6
XS GIS Cut Line= 3
     2143852.887      376165.994     2143493.073      375916.445
     2143475.663      375359.313
#Sta/Elev= 30
       0 2221.63    19.9 2212.85    59.7 2193.57    99.5 2177.66   129.4 2163.71
   149.3 2155.06   179.1 2143.46   218.9 2130.57   248.8 2122.06   268.7 2117.19
   318.5 2106.11   328.4  2104.5   348.3 2102.71   368.2 2099.68   437.9 2098.14
   507.6 2094.51   605.3 2091.52     617 2091.18   620.3  2091.5     627 2092.14
     637  2094.9   676.8 2112.06   686.7  2115.7   756.4 2138.24   816.1 2158.64
     846 2169.52   895.8 2188.32   915.7 2196.37   965.4  2217.4   995.3 2230.76
#Mann= 3 , 0 , 0
       0      .1       0   605.3    .045       0   620.3      .1       0
Bank Sta=605.3,620.3
XS Rating Curve= 0 ,0
Exp/Cntr=0.3,0.1

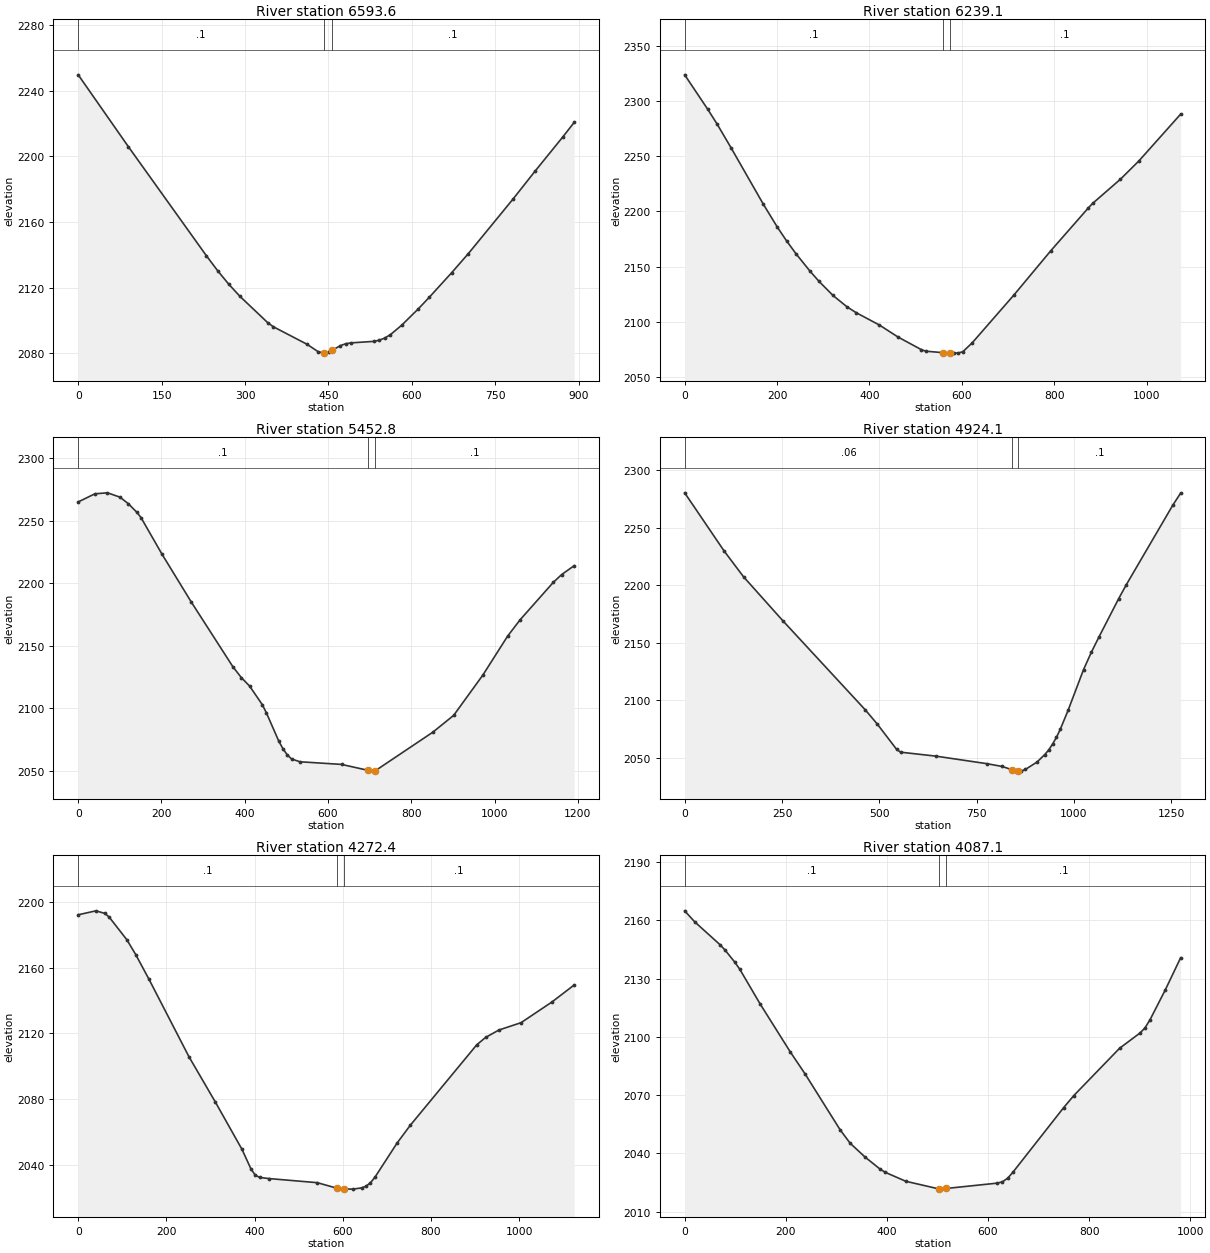
Type RM Length L Ch R = 1 ,6593.6  ,349.1,354.5,359.1
XS GIS Cut Line= 3
     2144160.471       375925.15     2143661.373      375646.584
     2143554.009      375344.804
#Sta/Elev= 30
       0  2249.8    90.2 2205.99   230.6 2139.45   250.7 2130.39   270.8  2122.1
   290.8 2114.74   340.9 2098.64     351 2096.16   411.1 2085.58   431.2 2081.05
   441.2  2080.1   441.5 2080.12   451.2 2080.81   456.5 2081.79   471.3 2084.64
   481.3 2085.86   491.4 2086.37   531.5 2087.26   541.5 2087.98   551.5 2089.33
   561.6 2091.39   581.6 2097.08   611.6 2107.08   631.6 2114.24   671.7 2129.17
   701.7 2140.82   781.8 2173.98   821.8 2191.14   871.9 2212.09   891.9 2220.78
#Mann= 3 , 0 , 0
       0      .1       0   441.5    .045       0   456.5      .1       0
Bank Sta=441.5,456.5
XS Rating Curve= 0 ,0
Exp/Cntr=0.3,0.1

Type RM Length L Ch R = 1 ,6239.1  ,797.3,786.3,772.2
XS GIS Cut Line= 2
      2144427.43      375838.098     2143619.008      375131.484
#Sta/Elev= 30
       0 2323.58    50.2  2292.2    70.2 2279.01   100.4 2257.52   170.6 2206.22
   200.7 2185.62   220.8 2173.15   240.8 2161.68   270.9 2146.06     291 2136.51
   321.1 2123.83   351.2 2113.61   371.3 2108.23   421.5 2097.06   461.6 2086.26
   511.8 2074.89   521.8 2073.36   558.6 2072.07   573.6 2071.74     582 2071.61
     592 2071.73   602.1 2072.86   622.2 2080.79   712.5 2124.09   792.7 2164.34
     873 2202.64     883  2207.1   943.3 2229.03   983.4 2245.63  1073.7 2287.96
#Mann= 3 , 0 , 0
       0      .1       0   558.6    .045       0   573.6      .1       0
Bank Sta=558.6,573.6
XS Rating Curve= 0 ,0
Exp/Cntr=0.3,0.1

Type RM Length L Ch R = 1 ,5452.8  ,512,528.7,545.7
XS GIS Cut Line= 3
     2144708.898       375388.33     2144531.892      374854.412
     2143931.234      374668.701
#Sta/Elev= 30
       0 2265.13    40.2 2271.64    70.3 2272.41   100.4 2268.94   120.5 2263.65
   140.6 2256.94   150.7 2252.66   200.9 2223.52   271.2 2185.23   371.6 2133.21
   391.7 2124.62   411.8 2117.72     442 2102.98     452 2096.36   482.1 2073.48
   492.2 2067.39   502.2 2062.71   512.3  2059.5   532.4 2057.21   632.4  2055.1
   695.2 2050.43   712.2 2049.72   851.9 2080.91   901.8 2094.34   971.7 2126.49
  1031.5 2157.79  1061.5 2170.86  1141.3 2200.85  1161.3 2207.03  1191.2 2214.11
#Mann= 3 , 0 , 0
       0      .1       0   695.2    .045       0   712.2      .1       0
Bank Sta=695.2,712.2
XS Rating Curve= 0 ,0
Exp/Cntr=0.3,0.1

Type RM Length L Ch R = 1 ,4924.1  ,663.2,651.6,639.8
XS GIS Cut Line= 3
     2145419.821      374805.083      2144795.95      374572.944
      2144494.17       374044.83
#Sta/Elev= 30
       0 2280.34   100.9 2230.01   151.3 2207.35   252.1 2169.24     464 2091.75
   494.2 2079.67   544.6 2057.38   554.7 2055.01   645.5 2051.57   775.4 2045.07
   815.2 2042.63   841.7 2039.69   855.1 2038.55   856.7 2038.58   865.1 2038.72
   875.1 2040.01     905 2046.43   924.9 2052.91   934.9 2056.89   944.9 2061.97
   954.8 2067.82   964.8  2074.9   984.8 2091.32  1024.6 2126.79  1044.6 2141.83
  1064.5 2155.34  1114.4 2188.15  1134.3 2200.45    1254 2269.72  1273.9 2280.07
#Mann= 3 , 0 , 0
       0     .06       0   841.7    .045       0   856.7      .1       0
Bank Sta=841.7,856.7
XS Rating Curve= 0 ,0
Exp/Cntr=0.3,0.1

Type RM Length L Ch R = 1 ,4272.4  ,185.1,185.4,185.6
XS GIS Cut Line= 2
     2145538.792      374216.032     2144566.713      373650.194
#Sta/Elev= 30
       0 2192.29    40.2  2194.7    60.3 2193.14    70.3 2190.87   110.5    2177
   130.6 2167.95   160.7 2152.89   251.1 2105.79   311.3    2078   371.6  2049.2
   391.7  2037.4   401.7 2033.48   411.8 2032.16   431.8 2031.49   542.3 2028.96
   586.9 2025.58   601.9 2025.14   622.6 2025.03   642.7 2025.77   652.8  2026.8
   662.8 2028.91   672.8 2032.22   723.1 2053.08   753.2 2063.98   903.8 2112.99
   923.9  2117.5     954 2122.02  1004.3  2126.5  1074.6 2139.15  1124.8 2149.48
#Mann= 3 , 0 , 0
       0      .1       0   586.9    .045       0   601.9      .1       0
Bank Sta=586.9,601.9
XS Rating Curve= 0 ,0
Exp/Cntr=0.3,0.1

Type RM Length L Ch R = 1 ,4087.1  ,337.2,339.2,340.2
XS GIS Cut Line= 3
     2145589.321      373870.536     2145206.678      373812.495
     2144697.204       373507.24
#Sta/Elev= 30
       0 2164.91    19.8 2159.25    69.5 2147.56    79.4 2144.85    99.2 2138.44
   109.2 2134.73   148.8 2117.15   208.4 2092.45   238.2  2080.9   307.6 2052.09
   327.5 2045.17   357.2 2038.02     387 2031.81   397.1 2030.21   437.4 2025.64
   502.8 2021.71   507.8  2021.6   517.8 2021.95   618.6  2024.7   628.6  2025.4
   638.7 2027.18   648.8 2030.17   749.4 2063.52   769.6 2069.77   860.2 2094.14
   900.4 2101.96   910.5 2104.65   920.5 2108.88   950.7 2124.26   980.9 2140.74
#Mann= 3 , 0 , 0
       0      .1       0   502.8    .045       0   517.8      .1       0
Bank Sta=502.8,517.8
XS Rating Curve= 0 ,0
Exp/Cntr=0.3,0.1

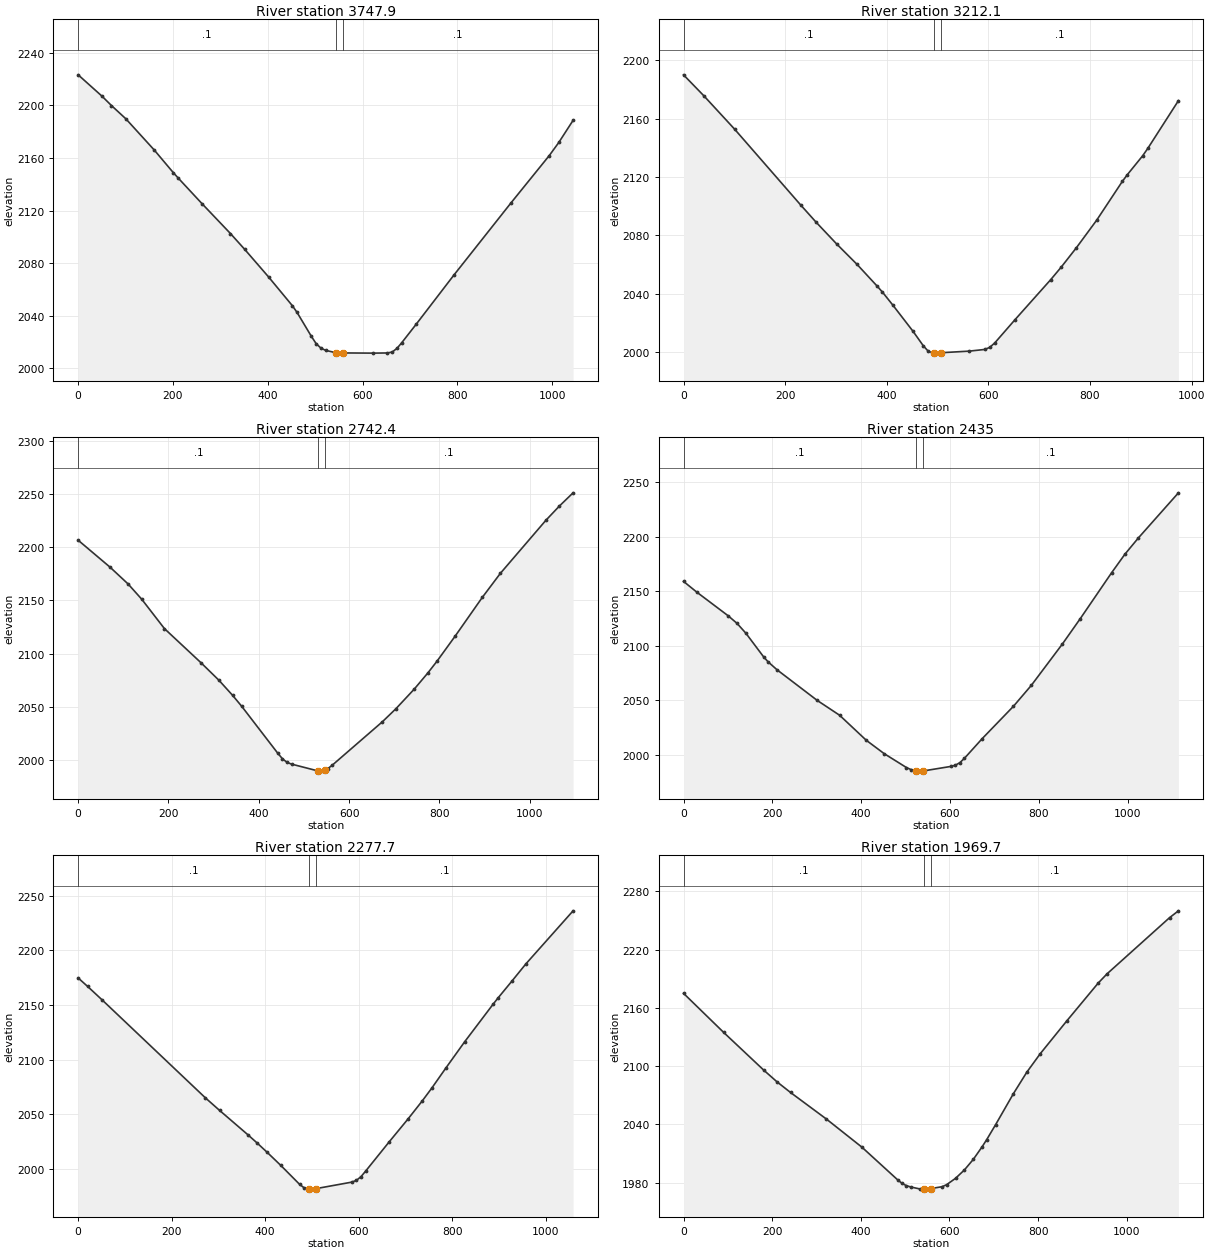
Type RM Length L Ch R = 1 ,3747.9  ,535.2,535.8,536.9
XS GIS Cut Line= 2
     2145715.798      373789.477     2144848.181      373209.131
#Sta/Elev= 30
       0 2223.24    50.2 2207.02    70.3 2199.85   100.4 2189.85   160.6 2165.99
   200.7 2148.81   210.8 2144.79     261 2125.31   321.2  2102.5   351.3 2090.44
   401.5 2069.52   451.6 2047.68   461.7 2042.47   491.8 2024.32   501.8  2018.8
   511.9 2015.36   521.9 2013.64   543.1 2011.87   558.1 2011.68   622.3 2011.53
   652.4 2011.66   662.4 2012.38   672.5  2015.2   682.5 2019.47   712.6 2033.37
   792.9 2071.13   913.3 2126.02   993.6 2161.83  1013.7  2171.8  1043.8 2188.61
#Mann= 3 , 0 , 0
       0      .1       0   543.1    .045       0   558.1      .1       0
Bank Sta=543.1,558.1
XS Rating Curve= 0 ,0
Exp/Cntr=0.3,0.1

Type RM Length L Ch R = 1 ,3212.1  ,472.8,469.6,466.2
XS GIS Cut Line= 2
     2145985.659      373348.414     2145184.781      372794.184
#Sta/Elev= 30
       0    2190    40.2 2175.57   100.4 2152.83   230.9 2100.69   261.1 2088.97
   301.2 2074.18   341.4 2060.16   381.6 2045.03   391.6 2041.08   411.7 2032.32
   451.8 2014.22   471.9 2004.35     482 2000.48     492 1999.31   492.4 1999.32
   507.4 1999.59   562.3 2000.68   592.4 2001.81   602.4 2003.19   612.5 2006.28
   652.6 2022.31   722.9 2049.75     743  2058.1   773.1 2071.48   813.3 2090.49
   863.5 2116.91   873.5 2121.61   903.7 2134.56   913.7 2139.58     974  2172.3
#Mann= 3 , 0 , 0
       0      .1       0   492.4    .045       0   507.4      .1       0
Bank Sta=492.4,507.4
XS Rating Curve= 0 ,0
Exp/Cntr=0.3,0.1

Type RM Length L Ch R = 1 ,2742.4  ,316.1,307.4,298.4
XS GIS Cut Line= 2
     2146233.921      372879.348     2145252.148      372392.399
#Sta/Elev= 30
       0 2206.56    70.4  2181.3   110.6 2165.43   140.8 2151.09     191 2123.51
   271.5 2091.61   311.7 2074.96   341.8 2060.85     362 2050.55   442.4 2006.15
   452.4 2001.15   462.5 1997.78   472.5 1996.14     532 1989.62   532.9 1989.55
   542.9 1989.91     547 1990.73     553 1991.93     563 1995.27   673.6 2035.92
   703.8 2048.28     744 2066.54   774.2 2081.75   794.3  2092.7   834.5 2116.26
   894.8 2152.78     935 2175.48  1035.6 2225.25  1065.7 2238.73  1095.9  2251.1
#Mann= 3 , 0 , 0
       0      .1       0     532    .045       0     547      .1       0
Bank Sta=532,547
XS Rating Curve= 0 ,0
Exp/Cntr=0.3,0.1

Type RM Length L Ch R = 1 ,2435    ,158.1,157.4,156.8
XS GIS Cut Line= 2
     2146418.043      372406.439     2145306.799      372325.663
#Sta/Elev= 30
       0 2159.12    30.1 2149.17   100.4 2127.53   120.4 2120.57   140.5 2111.44
   180.7 2089.56   190.7 2085.08   210.8  2077.8   301.1  2049.7   351.3 2036.13
   411.5 2013.08   451.7 2000.83   501.9 1988.04   511.9 1986.21   523.9 1985.06
     532 1984.74   538.9 1984.85   602.3 1989.09   612.3 1990.21   622.3 1992.58
   632.4  1996.5   672.5 2014.63   742.8 2044.34   782.9 2063.49   853.2 2101.69
   893.4 2124.98   963.6 2166.95   993.7 2184.08  1023.8 2198.92  1114.2 2240.49
#Mann= 3 , 0 , 0
       0      .1       0   523.9    .045       0   538.9      .1       0
Bank Sta=523.9,538.9
XS Rating Curve= 0 ,0
Exp/Cntr=0.3,0.1

Type RM Length L Ch R = 1 ,2277.7  ,316.4,307.9,298.6
XS GIS Cut Line= 2
      2146407.21      372233.868     2145349.919      372186.993
#Sta/Elev= 30
       0 2174.81    20.2 2167.03    50.4    2155   272.1 2064.81   302.4 2053.31
   362.9 2030.98     383 2023.29   403.2 2015.25   433.4 2002.81   473.7  1985.4
   483.8 1982.11   493.9  1981.1   494.1  1981.1     504 1981.25   509.1  1981.6
   584.6 1987.48   594.7 1989.03   604.8 1992.56   614.8 1997.67   665.2 2024.54
   705.6 2045.59   735.8 2062.02     756 2073.67   786.2 2092.15   826.5 2116.28
     887 2150.56   897.1 2156.07   927.3 2171.79   957.5 2187.77  1058.3 2236.37
#Mann= 3 , 0 , 0
       0      .1       0   494.1    .045       0   509.1      .1       0
Bank Sta=494.1,509.1
XS Rating Curve= 0 ,0
Exp/Cntr=0.3,0.1

Type RM Length L Ch R = 1 ,1969.7  ,477.5,488.7,500.1
XS GIS Cut Line= 2
     2146360.898      371728.004     2145312.565      372112.078
#Sta/Elev= 30
       0 2175.07    90.5 2134.81     181 2095.91   211.2 2083.75   241.4  2072.9
   321.9 2045.67   402.3 2016.59   482.8 1982.99   492.9 1979.27   502.9 1976.84
     513 1975.48   533.1 1973.48   543.2 1973.29   558.9 1973.93   583.4 1975.79
   593.4 1977.83   613.6  1984.4   633.7 1993.07   653.8 2003.97   673.9  2017.1
     684 2024.32   704.1 2039.73   744.3 2071.71   774.5 2093.82   804.7 2112.79
     865 2146.84   935.4 2185.56   955.5 2195.15  1096.4 2252.98  1116.5 2260.07
#Mann= 3 , 0 , 0
       0      .1       0   543.2    .045       0   558.9      .1       0
Bank Sta=543.2,558.9
XS Rating Curve= 0 ,0
Exp/Cntr=0.3,0.1

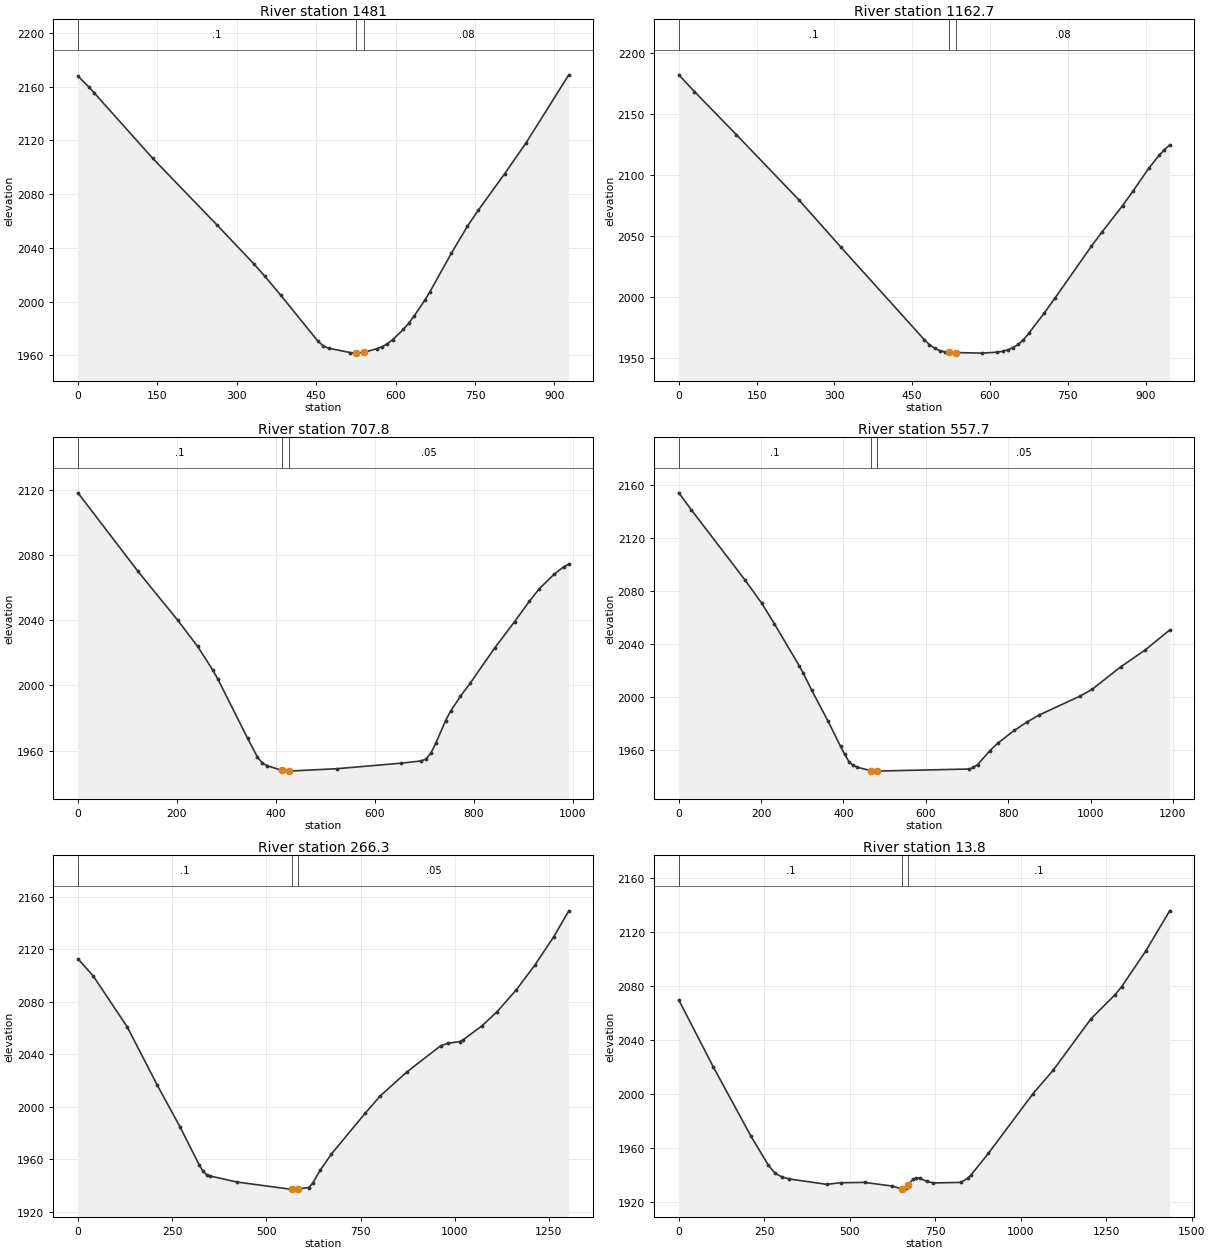
Type RM Length L Ch R = 1 ,1481    ,317,318.3,319.9
XS GIS Cut Line= 2
     2146330.964      371555.146     2145419.821      371383.944
#Sta/Elev= 30
       0 2167.94    20.2 2159.98    30.2 2155.65   141.1 2106.72     262 2057.31
   332.5 2027.99   352.7 2018.98   382.9 2004.81   453.5 1970.43   463.5 1966.96
   473.6 1965.26   513.9 1962.05     524 1961.62   525.9 1961.65   540.9 1962.35
   564.3 1964.87   574.4 1966.38   584.5 1968.67   594.6 1971.69   614.7 1979.27
   624.8 1983.93   634.8 1989.14     655 2000.94   665.1 2007.51   705.4 2036.09
   735.6 2056.07   755.8 2067.86   806.2 2095.36   846.5 2118.28   927.1 2168.86
#Mann= 3 , 0 , 0
       0      .1       0   525.9    .045       0   540.9     .08       0
Bank Sta=525.9,540.9
XS Rating Curve= 0 ,0
Exp/Cntr=0.3,0.1

Type RM Length L Ch R = 1 ,1162.7  ,439.6,454.8,469.7
XS GIS Cut Line= 2
     2146412.213      371262.071     2145483.659      371079.262
#Sta/Elev= 30
       0 2181.95    30.2 2168.23   110.8 2133.09   231.6 2079.67   312.1 2041.22
   473.2 1965.44   483.3 1961.29   493.3 1958.34   503.4 1956.41   513.5 1955.23
     520 1954.96     535 1954.84   583.9 1954.36   614.1 1955.16   624.2 1955.86
   634.3 1957.07   644.3 1958.93   654.4 1961.42   664.5 1965.27   674.6 1970.44
   704.8 1987.26   724.9  1999.1   795.4 2041.72   815.5 2053.15   855.8 2075.07
   875.9 2086.99   906.1 2105.51   926.2  2116.2   936.3 2120.72   946.4 2124.58
#Mann= 3 , 0 , 0
       0      .1       0     520    .045       0     535     .08       0
Bank Sta=520,535
XS Rating Curve= 0 ,0
Exp/Cntr=0.3,0.1

Type RM Length L Ch R = 1 ,707.8   ,147.6,150.2,152.1
XS GIS Cut Line= 3
      2146316.26      371076.093     2145951.474      370699.463
     2145520.363      370881.856
#Sta/Elev= 30
       0 2118.16     121 2070.13   201.7 2040.01     242 2023.96   272.2 2009.62
   282.3 2004.25   342.8 1967.72     363 1956.02   373.1  1952.3   383.2 1950.71
   411.7 1947.97   423.5 1947.45   426.7 1947.48   524.3 1948.95   653.8 1952.35
   693.6 1953.69   703.6 1954.89   713.6 1958.49   723.5 1964.59   743.4  1978.5
   753.4 1984.26   773.3 1993.34   793.2 2001.46     843 2023.18   882.9 2039.17
   912.8 2051.69   932.7 2059.32   962.6 2068.19   982.5 2072.87   992.4 2074.47
#Mann= 3 , 0 , 0
       0      .1       0   411.7    .045       0   426.7     .05       0
Bank Sta=411.7,426.7
XS Rating Curve= 0 ,0
Exp/Cntr=0.3,0.1

Type RM Length L Ch R = 1 ,557.7   ,288.6,291.4,307.5
XS GIS Cut Line= 3
     2146425.222      371019.243      2145958.58      370476.802
     2145489.569      370391.527
#Sta/Elev= 30
       0 2154.33    30.2 2141.55   161.2 2088.33   201.6 2070.85   231.8 2055.58
   292.3 2023.83   302.3 2018.18   322.5 2005.43   362.8  1981.7     393 1962.78
   403.1 1956.77   413.2 1951.42   423.3 1948.45   433.4 1947.12   467.4 1944.44
   473.7 1944.15   482.4 1944.21   705.5 1945.75   715.5 1946.99   725.5 1949.04
   755.3 1959.47   775.1  1965.4   814.8 1974.89   844.6 1981.03   874.4 1986.43
   973.8  2000.7  1003.6 2005.84  1073.1 2022.88  1132.6 2035.58  1192.2 2050.74
#Mann= 3 , 0 , 0
       0      .1       0   467.4    .045       0   482.4     .05       0
Bank Sta=467.4,482.4
XS Rating Curve= 0 ,0
Exp/Cntr=0.3,0.1

Type RM Length L Ch R = 1 ,266.3   ,250.3,252.5,254.5
XS GIS Cut Line= 3
     2146518.512      370862.994     2146132.582      370311.665
     2145523.218       370152.07
#Sta/Elev= 30
       0 2112.84    40.2 2099.89   130.6 2060.98   210.9 2016.29   271.2 1984.51
   321.4 1955.93   331.5 1951.01   341.5  1948.2   351.6 1947.16   421.9  1942.6
   562.5 1937.17     569 1937.18     584 1937.31   612.7 1938.41   622.8 1941.63
   642.8 1951.55     673 1964.02     763 1995.24     803 2008.42     873 2026.54
   962.9 2046.51   982.9 2048.52  1012.9 2049.64  1022.9 2051.15  1072.9 2061.84
  1112.9 2072.64  1162.9 2088.92  1212.9 2108.06  1262.9 2129.69  1302.9 2149.43
#Mann= 3 , 0 , 0
       0      .1       0     569    .045       0     584     .05       0
Bank Sta=569,584
XS Rating Curve= 0 ,0
Exp/Cntr=0.3,0.1

Type RM Length L Ch R = 1 ,13.8    ,19.6,13.8,8.3
XS GIS Cut Line= 3
     2146664.162      370781.444      2146272.92      370054.852
     2145667.627      369976.056
#Sta/Elev= 30
       0 2069.76   100.6 2020.42   211.3 1968.94   261.7 1947.72   281.8 1941.57
   301.9 1938.87     322 1937.46   432.7 1933.42     473 1934.61   543.4 1934.86
     624 1932.16   654.2 1929.89   664.2 1930.94     671 1933.12   684.3 1937.04
   694.4 1938.17   704.5 1937.96   724.6 1935.68   744.7 1934.48   825.2 1934.88
   845.2 1938.06   855.2 1940.52   905.3  1956.3  1035.4 2000.32  1095.4 2017.99
  1205.5 2055.87  1275.5 2073.58  1295.5 2079.74  1365.6    2106  1435.6 2135.74
#Mann= 3 , 0 , 0
       0      .1       0   654.2    .045       0     671      .1       0
Bank Sta=654.2,671
XS Rating Curve= 0 ,0
Exp/Cntr=0.3,0.1

Chan Stop Cuts=-1
Use User Specified Reach Order=0
Composite Channel Slope=5